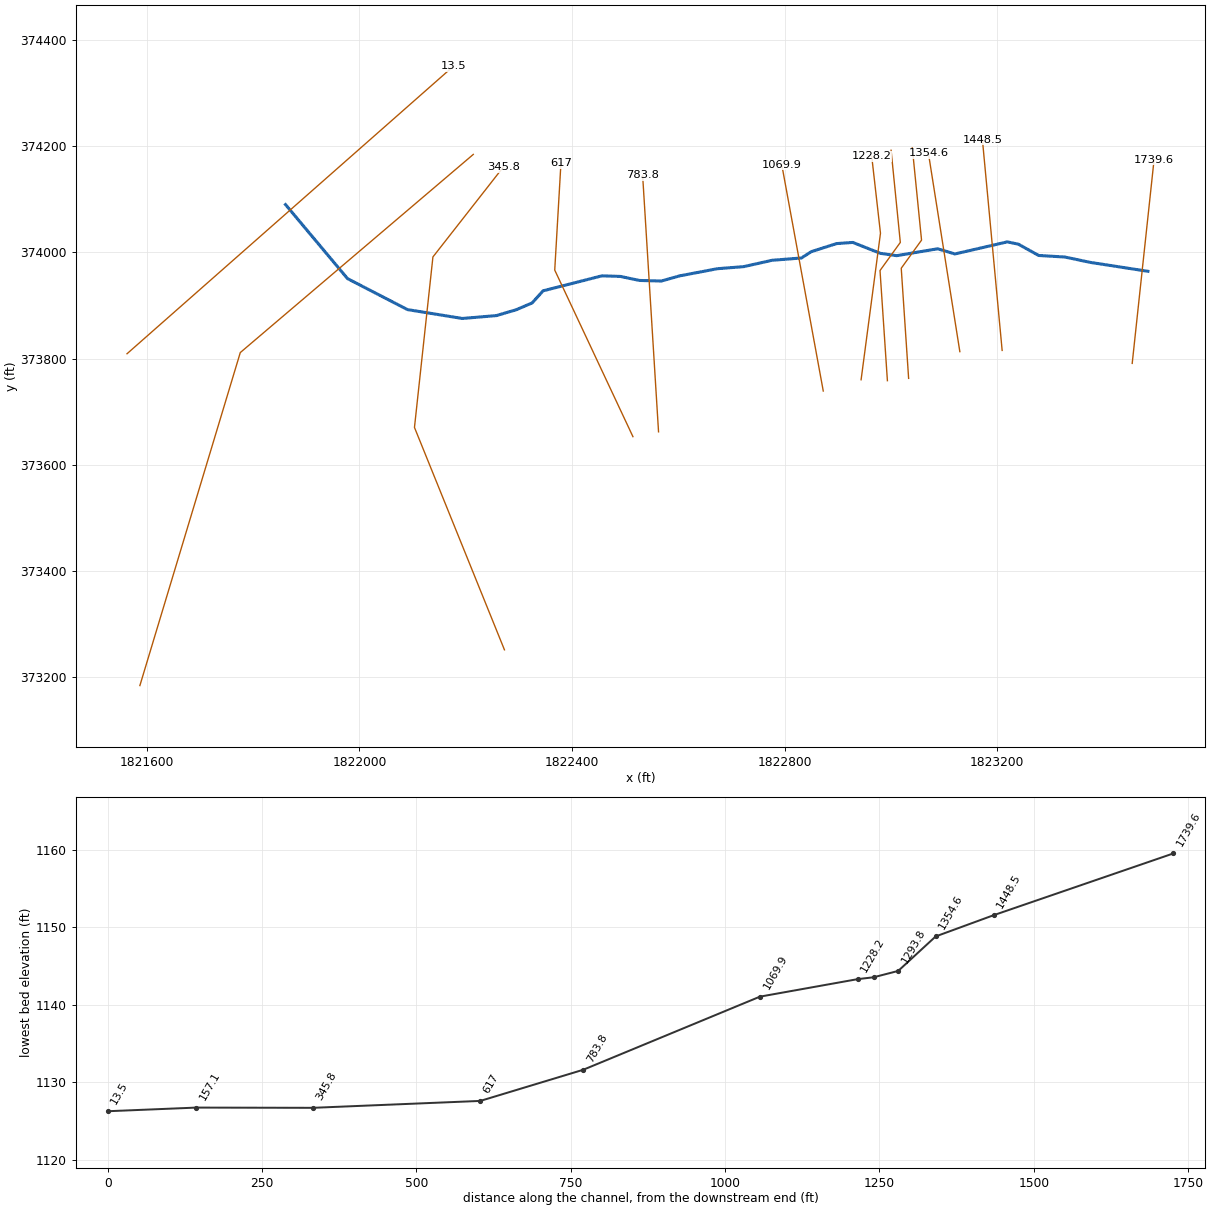
--- ROADFK.prj (project) ---

Proj Title=ROADFK
Current Plan=p01
Default Exp/Contr=0,0
English Units
Geom File=g01
Flow File=f01
Plan File=p01
BEGIN DESCRIPTION:
END DESCRIPTION:
DSS Export Rating Curves= 0
DSS Export Rating Curve Sorted= 0
DSS Export Volume Flow Curves= 0
DXF OffsetX= 0
DXF OffsetY= 0
DXF ScaleX= 0
DXF ScaleY= 0

--- ROADFK.p01 (plan) ---

Plan Title=Floodplain
Program Version=4.00
Geom File=g01
Flow File=f01
K Sum by GR=0
Std Step Tol=0.01
Critical Tol=0.01
Num of Std Step Trials=20
Max Error Tol=0.3
Flow Tol Ratio=0.001
Split Flow NTrial=30
Split Flow Tol=0.02
Split Flow Ratio=0.02
Log Output Level=0
Friction Slope Method=1
Unsteady Friction Slope Method=2
Unsteady Bridges Friction Slope Method=1
Global Log Level=0
CheckData=False
Run HTab=0
Run UNet=0
Run PostProcess=0
UNET Theta=0
UNET Theta Warmup=0
UNET ZTol=0
UNET ZSATol=0
UNET MxIter=0
UNET MaxInSteps=0
UNET DtIC=0
UNET DtMin=0
UNET MaxCRTS=0
UNET WFStab=0
UNET SFStab=0
UNET WFX=0
UNET SFX=0
UNET DSS MLevel=0
UNET DZMax Abort=0
UNET Convert EG Bridges=0
UNET Use Existing IB Tables=0
UNET Froude Limit=0
UNET Froude Power=0
Write IC File=0
Echo Input=False
Echo Output=False
Write Detailed=0

--- ROADFK.f01 (steady flow) ---

Flow Title=NFF Regression Equation
Program Version=4.10
Number of Profiles= 1
Profile Names=P100yr
River Rch & RM=ROADFK,Main            ,1739.6
872.1038
River Rch & RM=ROADFK,Main            ,157.1
896.8688
River Rch & RM=ROADFK,Main            ,13.5
1203.995
Boundary for River Rch & Prof#=ROADFK,Main            , 1
Up Type= 0
Dn Type= 1
Dn Known WS=1128.89
Set Internal Change=ROADFK          ,Main            ,13.5    , 1 , 3 ,1129.1
DSS Import GetInterval= 0
DSS Import GetPeak= 0
DSS Import FillOption= 0

--- ROADFK.g01 (geometry) ---

Geom Title=USGS 10m DEM
Program Version=4.10

River Reach=ROADFK          ,Main
Reach XY= 30
     1823483.417      373964.375     1823375.016      373981.182
     1823327.118      373991.266      1823277.96      373994.206
     1823239.709      374015.494     1823219.093      374019.834
     1823120.351      373997.048     1823087.799      374006.813
     1823010.759      373993.792     1822980.377      373998.133
     1822928.294      374018.749     1822897.912      374016.579
     1822850.169      374001.388     1822831.723      373989.452
     1822776.384      373985.112     1822723.216      373973.176
     1822673.596      373969.255     1822602.773      373955.815
     1822568.051      373946.049     1822526.818      373947.134
     1822491.011       373954.73     1822456.288      373955.815
     1822345.611      373927.603     1822324.995      373904.817
     1822294.613      373891.796     1822257.721      373880.945
     1822193.702       373875.52     1822090.444      373892.257
     1821977.666      373950.591     1821861.024      374090.053

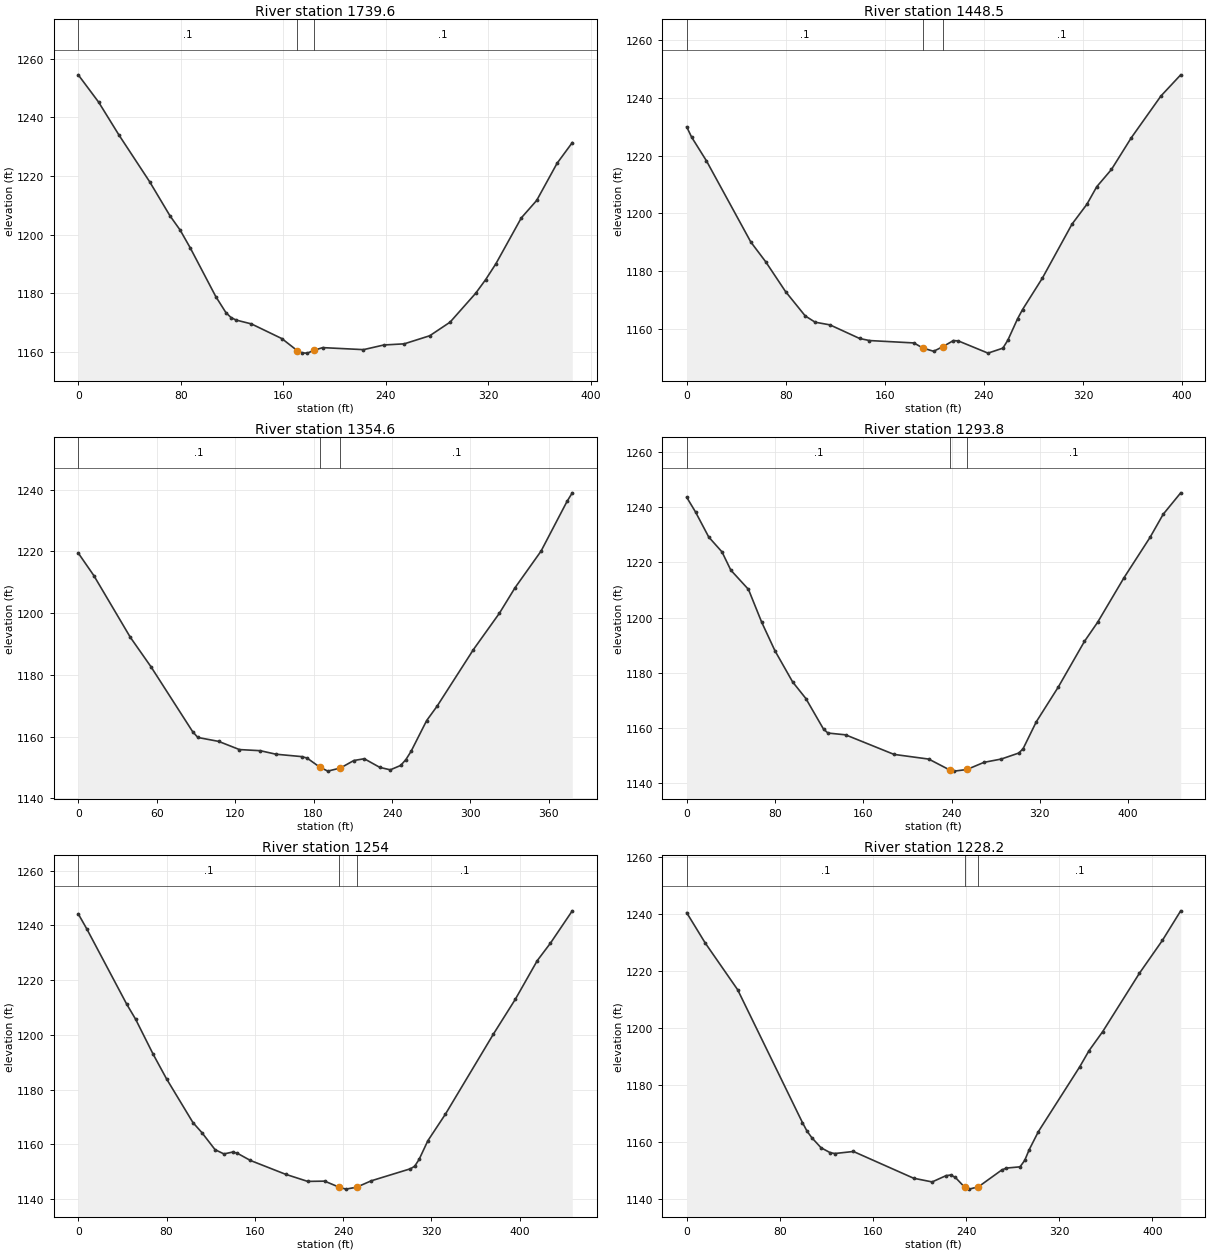
Type RM Length L Ch R = 1 ,1739.6  ,286.3,291.2,295.6
XS GIS Cut Line= 2
     1823453.944      373790.882     1823495.071      374174.389
#Sta/Elev= 30
       0 1254.53    15.9 1245.22    31.8 1233.98    55.7 1218.08    71.6 1206.43
    79.5 1201.58    87.5 1195.43   107.4 1178.84   115.3 1173.37   119.3 1171.69
   123.3 1170.83   135.2 1169.52     159  1164.5     171  1160.4     175  1159.6
   178.9 1159.55   184.2 1160.55   190.9 1161.43   222.7 1160.74   238.6 1162.33
   254.5 1162.72   274.4 1165.48   290.3 1170.12   310.2 1179.94   318.1 1184.66
   326.1 1190.08   345.9  1205.7   357.9 1211.66   373.8 1224.32   385.7  1231.4
#Mann= 3 , 0 , 0
       0      .1       0     171    .045       0   184.2      .1       0
Bank Sta=171,184.2
XS Rating Curve= 0 ,0
Exp/Cntr=0.3,0.1

Type RM Length L Ch R = 1 ,1448.5  ,92,93.9,95.9
XS GIS Cut Line= 2
     1823209.263      373815.329      1823172.12      374212.472
#Sta/Elev= 30
       0 1229.98       4 1226.42      16 1218.18    51.8 1190.07    63.8 1183.24
    79.8 1172.93    95.7 1164.48   103.7  1162.3   115.7 1161.37   139.6 1156.66
   147.6 1155.94   183.5 1155.11   190.7 1153.34   199.4 1152.22   206.7 1153.79
   215.4 1155.94   219.4  1155.8   243.3 1151.58   255.3  1153.3   259.3 1156.05
   267.2 1163.51   271.2 1166.69   287.2 1177.57   311.1 1196.26   323.1 1203.13
   331.1 1209.24     343 1215.23     359 1226.21   382.9 1240.66   398.9 1248.01
#Mann= 3 , 0 , 0
       0      .1       0   190.7    .045       0   206.7      .1       0
Bank Sta=190.7,206.7
XS Rating Curve= 0 ,0
Exp/Cntr=0.3,0.1

Type RM Length L Ch R = 1 ,1354.6  ,84.4,60.7,38.9
XS GIS Cut Line= 2
     1823129.662      373813.036     1823070.634      374186.299
#Sta/Elev= 30
       0 1219.48    11.9 1212.19    39.8 1192.21    55.7  1182.6    87.5 1161.63
    91.5 1159.74   107.4 1158.47   123.3 1155.82   139.2 1155.46   151.2 1154.32
     171 1153.54     175 1153.08   184.6 1150.18   190.9 1148.84   200.6 1149.86
   210.8 1152.28   218.8 1152.85   230.7 1150.05   238.7 1149.26   246.6 1150.68
   250.6 1152.56   254.6 1155.26   266.5 1165.21   274.5 1169.88   302.3 1188.22
   322.2 1200.01   334.2 1208.29     354 1220.09   373.9 1236.21   377.9 1238.97
#Mann= 3 , 0 , 0
       0      .1       0   184.6    .045       0   200.6      .1       0
Bank Sta=184.6,200.6
XS Rating Curve= 0 ,0
Exp/Cntr=0.3,0.1

Type RM Length L Ch R = 1 ,1293.8  ,35.8,39.9,40.7
XS GIS Cut Line= 4
     1823033.308      373762.688     1823019.419      373970.154
     1823057.613      374023.105     1823040.252      374196.716
#Sta/Elev= 30
       0 1243.62       8 1238.29      20  1229.2      32 1223.82      40 1217.21
      56 1210.23      68 1198.32      80    1188      96 1176.72     108  1170.7
     124 1159.62     128 1158.19     144 1157.54   187.9 1150.45   219.4 1148.75
   238.6 1144.76   242.5 1144.39     254 1144.98   269.4 1147.57   285.1 1148.77
     301 1150.95   304.9 1152.54   316.8 1162.25   336.7 1174.82   360.5 1191.42
   372.4 1198.32   396.2 1214.39   419.9 1229.08   431.8 1237.45   447.7 1245.22
#Mann= 3 , 0 , 0
       0      .1       0   238.6    .045       0     254      .1       0
Bank Sta=238.6,254
XS Rating Curve= 0 ,0
Exp/Cntr=0.3,0.1

Type RM Length L Ch R = 1 ,1254    ,13.3,25.8,39.5
XS GIS Cut Line= 4
     1822993.377      373758.348     1822979.488      373965.813
     1823017.683      374018.765     1823000.322      374192.376
#Sta/Elev= 30
       0 1244.26       8 1238.56      44 1211.16      52 1205.71      68 1192.82
      80 1183.92     104 1167.88     112 1164.27     124    1158     132 1156.45
     140 1157.13     144 1156.73     156 1154.06   187.9    1149   207.9  1146.4
   223.3 1146.49   236.2 1144.32   242.5 1143.57   252.2 1144.26   265.5 1146.61
     301 1151.01   304.9 1151.95   308.9 1154.45   316.8 1161.26   332.7 1170.97
   376.3 1200.33   396.2 1213.09     416 1227.17   427.9 1233.53   447.7 1245.36
#Mann= 3 , 0 , 0
       0      .1       0   236.2    .045       0   252.2      .1       0
Bank Sta=236.2,252.2
XS Rating Curve= 0 ,0
Exp/Cntr=0.3,0.1

Type RM Length L Ch R = 1 ,1228.2  ,151.1,158.3,165.3
XS GIS Cut Line= 3
     1822943.898      373760.084     1822980.356      374036.126
     1822963.863      374181.091
#Sta/Elev= 30
       0 1240.41    15.9 1229.78    43.8 1213.34    99.4 1166.72   103.4 1163.67
   107.4 1161.43   115.4 1157.86   123.3 1156.12   127.3 1155.84   143.2 1156.55
   194.9 1147.16   210.8 1145.86   222.8 1148.07   226.7 1148.28   230.7 1147.46
   238.7 1144.03   242.6 1143.33   250.6 1144.16   270.5 1150.02   274.5 1150.72
   286.3 1151.16   290.3 1153.41   294.2 1157.21   302.1 1163.56   337.6 1186.31
   345.5 1191.92   357.3 1198.65   388.8 1219.12   408.6  1230.7   424.3 1241.06
#Mann= 3 , 0 , 0
       0      .1       0   238.7    .045       0   250.6      .1       0
Bank Sta=238.7,250.6
XS Rating Curve= 0 ,0
Exp/Cntr=0.3,0.1

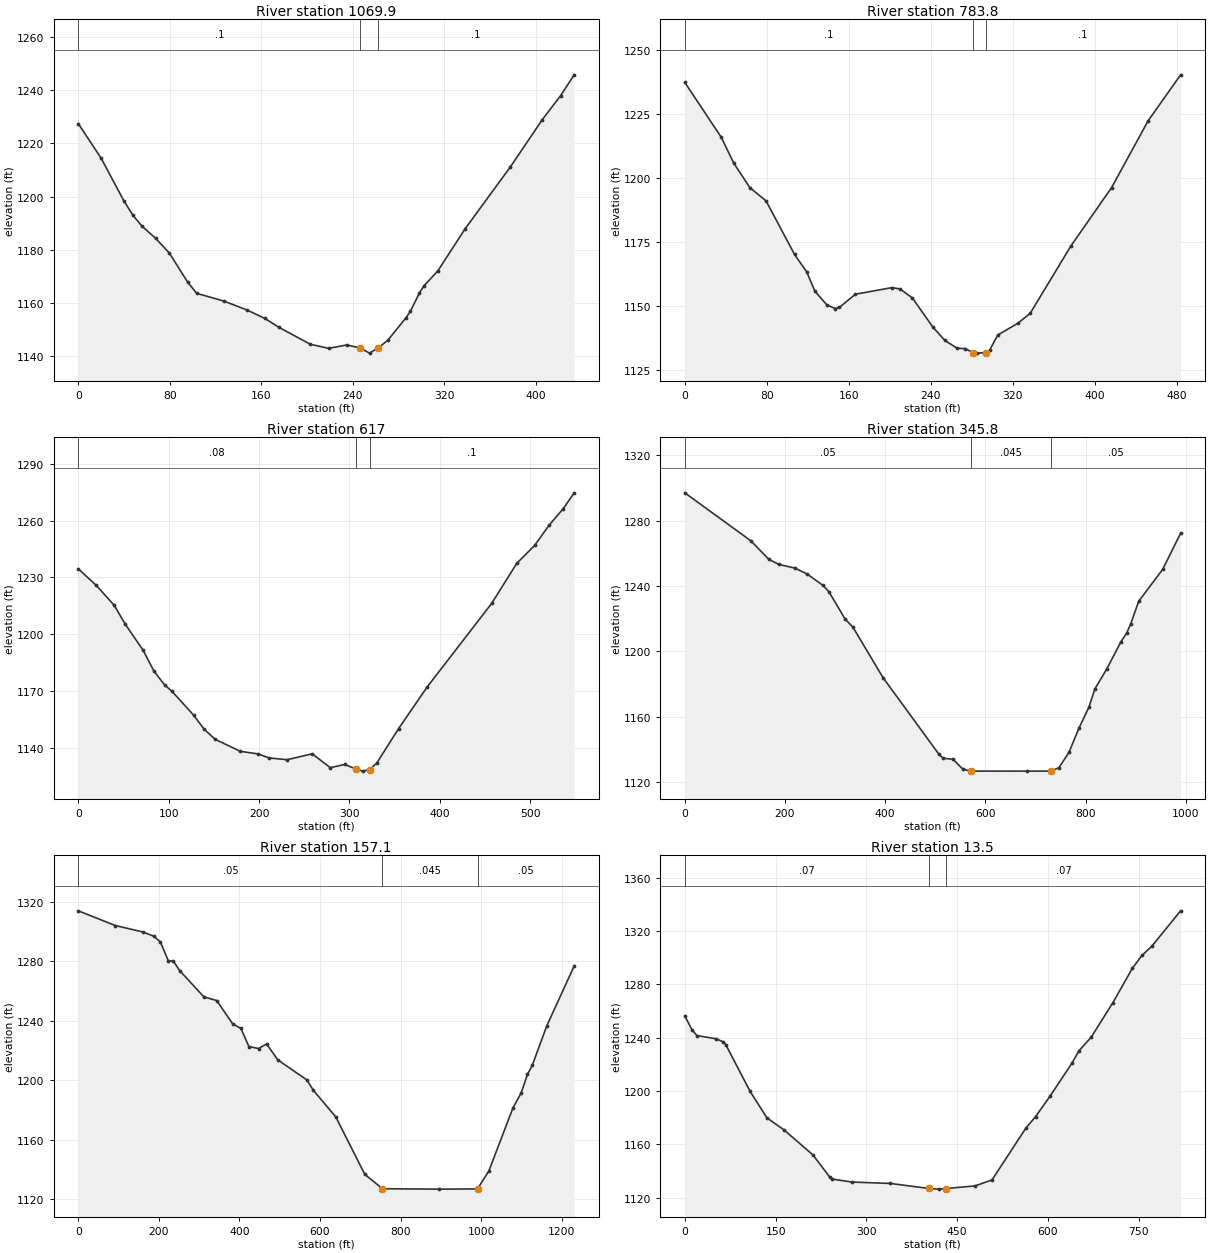
Type RM Length L Ch R = 1 ,1069.9  ,288.8,286.1,283.2
XS GIS Cut Line= 2
     1822872.717      373738.817     1822794.592      374165.466
#Sta/Elev= 30
       0 1227.39    19.9 1214.44    39.8 1198.39    47.8 1192.91    55.7 1188.84
    67.6 1184.28    79.6 1178.73    95.5 1167.88   103.5 1163.57   127.3 1160.66
   147.2 1157.36   163.2 1154.11   175.1 1150.87   202.9 1144.41   218.9 1142.87
   234.8 1144.15   246.7 1142.98   254.7 1141.07   262.3 1143.06   270.6 1145.86
   286.5 1154.32   290.5 1156.86   298.4 1163.74   302.4 1166.43   314.4 1171.98
   338.2 1187.78     378  1211.2   405.9 1228.96   421.8  1237.9   433.7 1245.78
#Mann= 3 , 0 , 0
       0      .1       0   246.7    .045       0   262.3      .1       0
Bank Sta=246.7,262.3
XS Rating Curve= 0 ,0
Exp/Cntr=0.3,0.1

Type RM Length L Ch R = 1 ,783.8   ,158.1,166.8,175.6
XS GIS Cut Line= 2
     1822562.822      373661.994     1822532.874      374145.067
#Sta/Elev= 30
       0 1237.37    35.7 1215.86    47.6 1205.98    63.5 1196.26    79.3  1191.1
   107.1  1170.2     119 1163.37     127 1155.83   138.8 1150.41   146.8 1149.06
   150.8 1149.47   166.6 1154.65   202.3 1157.23   210.3 1156.67   222.2 1153.16
     242 1141.88   253.9 1136.58   265.8 1133.56   273.7 1133.39   281.7 1131.78
   285.6 1131.64   293.6 1131.81   297.5 1132.75   305.5 1138.72   325.3 1143.34
   337.2 1147.22   376.9 1173.49   416.6 1196.28   452.3 1222.38     484 1240.32
#Mann= 3 , 0 , 0
       0      .1       0   281.7    .045       0   293.6      .1       0
Bank Sta=281.7,293.6
XS Rating Curve= 0 ,0
Exp/Cntr=0.3,0.1

Type RM Length L Ch R = 1 ,617     ,283.6,271.2,258.7
XS GIS Cut Line= 3
     1822514.644      373652.879     1822367.509      373966.681
     1822379.228      374168.504
#Sta/Elev= 30
       0 1234.49    19.9 1225.72    39.8 1215.18    51.8 1205.33    71.7 1191.47
    83.7 1180.46    95.6  1173.1   103.6 1169.82   127.5 1157.25   139.4 1149.66
   151.4 1144.44   179.3 1138.08   199.2  1136.7   211.1  1134.6   231.1 1133.65
   258.9 1136.78   278.9 1129.43   294.8 1131.15   306.8 1128.83   314.7 1127.62
   322.7 1128.46   330.6 1132.09   354.5 1150.11   386.2 1172.14   457.6 1216.29
   485.3 1237.37   505.1 1246.88     521 1257.51   536.9 1266.36   548.8 1274.64
#Mann= 3 , 0 , 0
       0     .08       0   306.8    .045       0   322.7      .1       0
Bank Sta=306.8,322.7
XS Rating Curve= 0 ,0
Exp/Cntr=0.3,0.1

Type RM Length L Ch R = 1 ,345.8   ,206.3,188.7,171.1
XS GIS Cut Line= 4
     1822272.891      373251.404      1822103.62       373670.24
     1822138.342      373991.421     1822270.721      374160.692
#Sta/Elev= 30
       0 1297.07   131.9  1267.7   167.9 1256.31   187.9 1253.24   219.9 1250.98
   243.9 1247.44   275.8 1240.41   287.8 1236.47   319.8 1219.93   335.8 1214.73
   395.8 1183.89   507.6 1136.92   515.6 1134.62   535.5 1133.98   555.4 1127.81
   571.4 1126.75   683.1 1126.73   730.9 1126.75   746.9 1128.87   766.8 1138.21
   786.7 1152.96   806.6 1165.86   818.6 1177.09   842.4  1189.3   870.3 1205.76
   882.2 1211.35   890.2 1216.98   906.1 1230.74   953.9 1250.22   989.7 1272.38
#Mann= 3 , 0 , 0
       0     .05       0   571.4    .045       0   730.9     .05       0
Bank Sta=571.4,730.9
XS Rating Curve= 0 ,0
Exp/Cntr=0.3,0.1

Type RM Length L Ch R = 1 ,157.1   ,143.2,143.6,144
XS GIS Cut Line= 3
     1821587.033      373184.042     1821775.929      373811.299
     1822214.297      374184.563
#Sta/Elev= 30
       0 1313.98    91.9 1304.08   159.8  1299.8   187.7 1296.86   203.7 1292.98
   223.7 1280.21   235.7 1280.25   251.6 1273.75   311.6 1256.13   343.5 1253.61
   383.5 1237.82   403.4 1234.91   423.4 1222.67   447.4 1221.36   467.4  1224.4
   495.3 1213.66   567.2 1200.23   583.2 1193.34   639.1 1175.34   711.1 1136.71
     755 1127.02     895 1126.76   990.9 1126.89  1018.9 1138.89  1078.9 1181.39
  1098.9 1191.26  1114.9  1203.9  1126.9 1210.13  1162.9 1236.64  1230.8 1276.86
#Mann= 3 , 0 , 0
       0     .05       0     755    .045       0   990.9     .05       0
Bank Sta=755,990.9
XS Rating Curve= 0 ,0
Exp/Cntr=0.3,0.1

Type RM Length L Ch R = 1 ,13.5    ,14.1,13.5,12.9
BEGIN DESCRIPTION:
set elevation (common XS with whiteoakck)
END DESCRIPTION:
XS GIS Cut Line= 2
     1821562.822      373809.076     1822177.059      374350.809
#Sta/Elev= 30
       0 1256.31      12 1245.77      20 1241.52    51.9 1239.09    63.9 1236.71
    67.9 1234.52   107.9 1199.61   135.8 1179.72   163.8 1170.76   211.7 1151.95
   239.7 1135.15   243.7 1133.84   275.7 1131.61   339.6 1130.55   403.5 1126.77
   419.5 1126.29   431.5 1126.75   479.4 1128.71   507.4 1133.18   563.3 1172.02
   579.3 1180.66   603.3 1196.04   639.2 1220.62   651.2 1230.17   671.2 1240.27
   707.1 1266.22   739.1 1291.89   755.1 1301.66   771.1 1308.43     819 1335.14
#Mann= 3 , 0 , 0
       0     .07       0   403.5    .045       0   431.5     .07       0
Bank Sta=403.5,431.5
XS Rating Curve= 0 ,0
Exp/Cntr=0.3,0.1

Chan Stop Cuts=-1
Use User Specified Reach Order=0
Composite Channel Slope=5